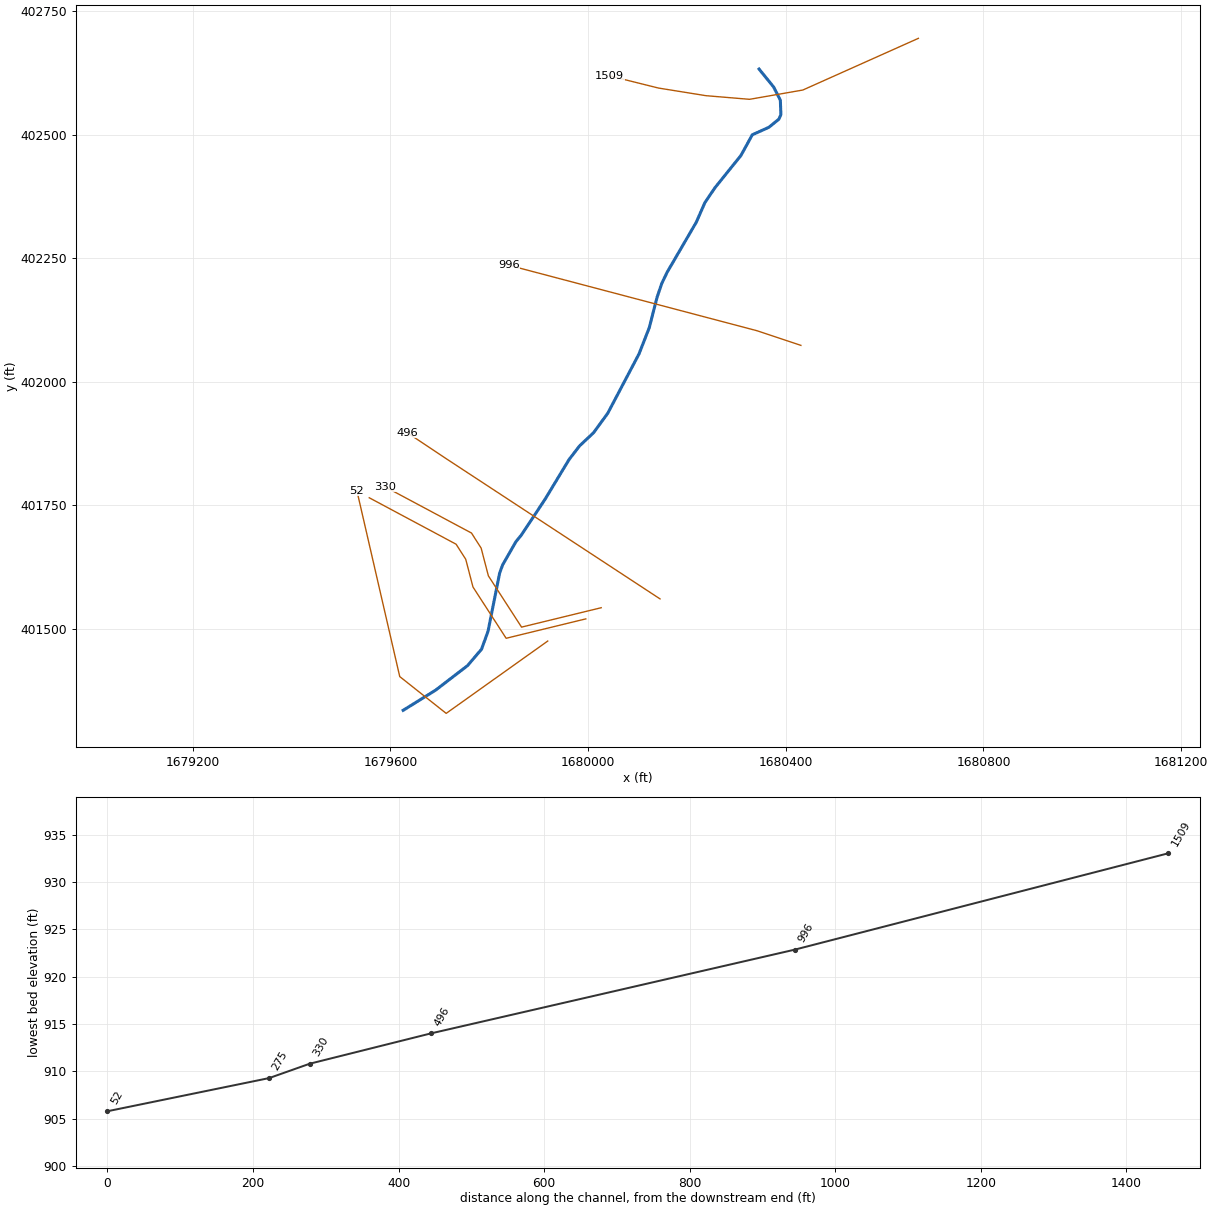
--- RACCOONRN.prj (project) ---

Proj Title=RACCOONRN
Current Plan=p01
Default Exp/Contr=0,0
English Units
Geom File=g01
Flow File=f01
Plan File=p01
BEGIN DESCRIPTION:
---------- MODELED AS PART OF WVEMD CTP PROGRAM, 2023----------
Stream Name: Raccoon Run
Flood Zone:  AFH
Wetzel County, WV
HEC-RAS Version: RAS 6.3
Vertical Datum: NAVD88
Projection: NAD 1983 StatePlane West Virginia S FIPS 4702 (US Feet)
Terrain: 1-meter West Virginia FEMA R3 South Central (collected 2018-2020)
Land Use: 2019 NLCD
Hydrologic Method:
WV SIR2010-5033 regression equations
Additional Model Notes:
None
END DESCRIPTION:
DSS File=dss
DSS Export Rating Curves= 0
DSS Export Rating Curve Sorted= 0
DSS Export Volume Flow Curves= 0
DXF OffsetX= 0
DXF OffsetY= 0
DXF ScaleX= 0
DXF ScaleY= 0

--- RACCOONRN.p01 (plan) ---

Plan Title=Floodplain
Program Version=6.30
Short Identifier=Floodplain
Geom File=g01
Flow File=f01
Subcritical Flow
K Sum by GR= 0
Std Step Tol= 0.01
Critical Tol= 0.01
Num of Std Step Trials= 20
Max Error Tol= 0.3
Flow Tol Ratio= 0.001
Split Flow NTrial= 30
Split Flow Tol= 0.02
Split Flow Ratio= 0.02
Log Output Level= 0
Friction Slope Method= 1
Unsteady Friction Slope Method= 2
Unsteady Bridges Friction Slope Method= 1
Parabolic Critical Depth
Global Vel Dist= 0 , 0 , 0
Global Log Level= 0
CheckData=True
Encroach Param=-1 ,0,0, 0
Computation Interval=0.1SEC
Output Interval=1SEC
Instantaneous Interval=Max Profile
Mapping Interval=1HOUR
Computation Time Step Use Courant=        0
Computation Time Step Use Time Series=    0
Computation Time Step Count To Double=0
Computation Time Step Max Doubling=0
Computation Time Step Max Halving=0
Computation Time Step Residence Courant=0
Run HTab= 0
Run UNet= 0
Run Sediment= 0
Run PostProcess= 0
Run WQNet= 0
Run RASMapper=-1
UNET Theta= 0
UNET Theta Warmup= 0
UNET ZTol= 0
UNET ZSATol= 0
UNET MxIter= 0
UNET Max Iter WO Improvement= 0
UNET MaxInSteps= 0
UNET DtIC= 0
UNET DtMin= 0
UNET MaxCRTS= 0
UNET WFStab= 0
UNET SFStab= 0
UNET WFX= 1
UNET SFX= 1
UNET Gravity=32.17405
UNET 1D Methodology=Finite Difference
UNET DSS MLevel= 1
UNET Pardiso=0
UNET DZMax Abort= 0
UNET Use Existing IB Tables= 0
UNET Froude Reduction=False
UNET Froude Limit= 0
UNET Froude Power= 0
UNET D1 Cores= 0
UNET WindReference=Eulerian
UNET WindDragFormulation=Hsu (1988)
UNET D2 Coriolis=0
UNET D2 Cores= 0
UNET D2 Theta= 1
UNET D2 Theta Warmup= 1
UNET D2 Z Tol= 0.01
UNET D2 Volume Tol= 0.01
UNET D2 Max Iterations= 20
UNET D2 Equation= 0
UNET D2 RampUpFraction=0.1
UNET D2 TimeSlices= 1
UNET D2 Turbulence Formulation=Non-Conservative (original)
UNET D2 Eddy Viscosity=0.3
UNET D2 Transverse Eddy Viscosity=0.1
UNET D2 Smagorinsky Mixing=0
UNET D2 BCVolumeCheck=0
UNET D2 Cores=0
UNET D2 SolverType=PARDISO (Direct)
UNET D2 Minimum Iterations= 3
UNET D2 Maximum Iterations= 30
UNET D2 Restart Number= 10
UNET D2 Relaxation Coeff=1.3
UNET D2 SOR Precondition Iterations= 10
UNET D2 ILUT Maximum Fill= 8
UNET D2 ILUT Tolerance=1E-08
UNET D2 Convergence Tolerance=0.00001
UNET D1D2 MaxIter= 0
UNET D1D2 ZTol=0.01
UNET D1D2 QTol=0.1
UNET D1D2 MinQTol=1
DSS File=dss
Write IC File= 0
Write IC File at Fixed DateTime=0
Write IC File at Sim End=0
Echo Input=False
Echo Parameters=False
Echo Output=False
Write Detailed= 0
HDF Write Warmup=0
HDF Write Time Slices=0
HDF Flush=0
HDF Compression= 1
HDF Chunk Size= 1
HDF Spatial Parts= 1
HDF Use Max Rows=0
HDF Fixed Rows= 1
Calibration Method= 0
Calibration Iterations= 20
Calibration Max Change=0.05
Calibration Tolerance=0.2
Calibration Maximum=1.5
Calibration Minimum=0.5
Calibration Optimization Method= 1
WQ AD Non Conservative
WQ ULTIMATE=-1
WQ Max Comp Step=1HOUR
WQ Output Interval=15MIN
WQ Output Selected Increments= 0
WQ Output face flow=0
WQ Output face velocity=0
WQ Output face area=0
WQ Output face dispersion=0
WQ Output cell volume=0
WQ Output cell surface area=0
WQ Output cell continuity=0
WQ Output cumulative cell continuity=0
WQ Output face conc=0
WQ Output face dconc_dx=0
WQ Output face courant=0
WQ Output face peclet=0
WQ Output face adv mass=0
WQ Output face disp mass=0
WQ Output cell mass=0
WQ Output cell source sink temp=0
WQ Output nsm pathways=0
WQ Output nsm derived pathways=0
WQ Create Restart=0
WQ Fixed Restart=0
WQ System Summary=0
WQ Write To DSS=0
Sorting and Armoring Iterations= 10
XS Update Threshold= 0.02
Bed Roughness Predictor= 0
Hydraulics Update Threshold= 0.02
Energy Slope Method= 1
Volume Change Method= 1
Sediment Retention Method= 0
Sediment TS Multiplier= 1
Warm Up Method= 0
XS Weighting Method= 0
Number of US Weighted Cross Sections= 1
Number of DS Weighted Cross Sections= 1
Upstream XS Weight=0
Main XS Weight=1
Downstream XS Weight=0
Number of DS XS's Weighted with US Boundary= 1
Upstream Boundary Weight= 1
Weight of XSs Associated with US Boundary= 0
Number of US XS's Weighted with DS Boundary= 1
Downstream Boundary Weight= 0.5
Weight of XSs Associated with DS Boundary= 0.5
Percentile Method= 0
Sediment Output Level= 3
Mass or Volume Output= 0
Output Increment Type= 1
Profile and TS Output Increment= 1
Transport Output Increment 1
XS Output Flag= 0
XS Output Increment= 10
Read HDF5 Sediment Hotstart= 0
Sediment Hotstart Type= 0
Write Gradation File= 0
Read Gradation Hotstart= 0
Write HDF5 File= 1
Write Binary Output= 1
Write DSS Sediment File= 0
DSS Sediment Output Type= 1
SV Curve= 0
Specific Gage Flag= 0
Subcell Erosion Methods= 0
Subcell Deposition Methods= 0
Advection Scheme= 1
Matrix Solver= 0
Implicit Weighting Factor= 1
Maximum Outer Loop Convergence Iterations= 5
Convergence Maximum Absolute= 0.001
Convergence RMSE= 0.0001
Grain Fractions Max Abs Error= 0.001
Max Subgrid Regions= 1
Max Subgrid Length Scale= 3.402823E+38
Initial Layer Thickness= 3.402823E+38
Min Layer Thickness= 3.402823E+38
Max Layer Thickness= 3.402823E+38
Number of Layers= 5

--- RACCOONRN.f01 (steady flow) ---

Flow Title=Flow
Program Version=6.31
Number of Profiles= 1
Profile Names=F01pct
River Rch & RM=RACCOONRN,Main,1509
     575
Boundary for River Rch & Prof#=RACCOONRN,Main            , 1
Up Type= 0
Dn Type= 3
Dn Slope=0.01566
DSS Import GetInterval= 0
DSS Import GetPeak= 0
DSS Import FillOption= 0

--- RACCOONRN.g01 (geometry) ---

Geom Title=Geometry
Program Version=6.30

River Reach=RACCOONRN       ,Main
Reach XY= 30
     1680345.883      402632.618     1680375.488       402596.16
      1680388.92       402569.57     1680390.016      402540.513
     1680385.905      402531.193      1680365.62      402514.746
     1680332.177       402499.67     1680309.151      402457.729
     1680256.794      402392.763     1680236.236      402362.336
     1680218.709      402322.486      1680160.03      402221.832
     1680148.894      402198.703     1680139.471      402170.863
     1680123.624      402109.187     1680103.065      402056.504
     1680039.675      401936.149     1680010.978      401896.744
     1679982.709      401870.189     1679961.293      401842.349
     1679912.894      401762.254     1679864.924      401689.869
     1679853.787      401676.163     1679826.804      401629.049
     1679820.808      401612.3451679797.44033558401495.075536385
1679784.25614645401458.6350320381679755.96591662401425.496393428
1679691.22940951401375.729763658     1679625.597      401334.956

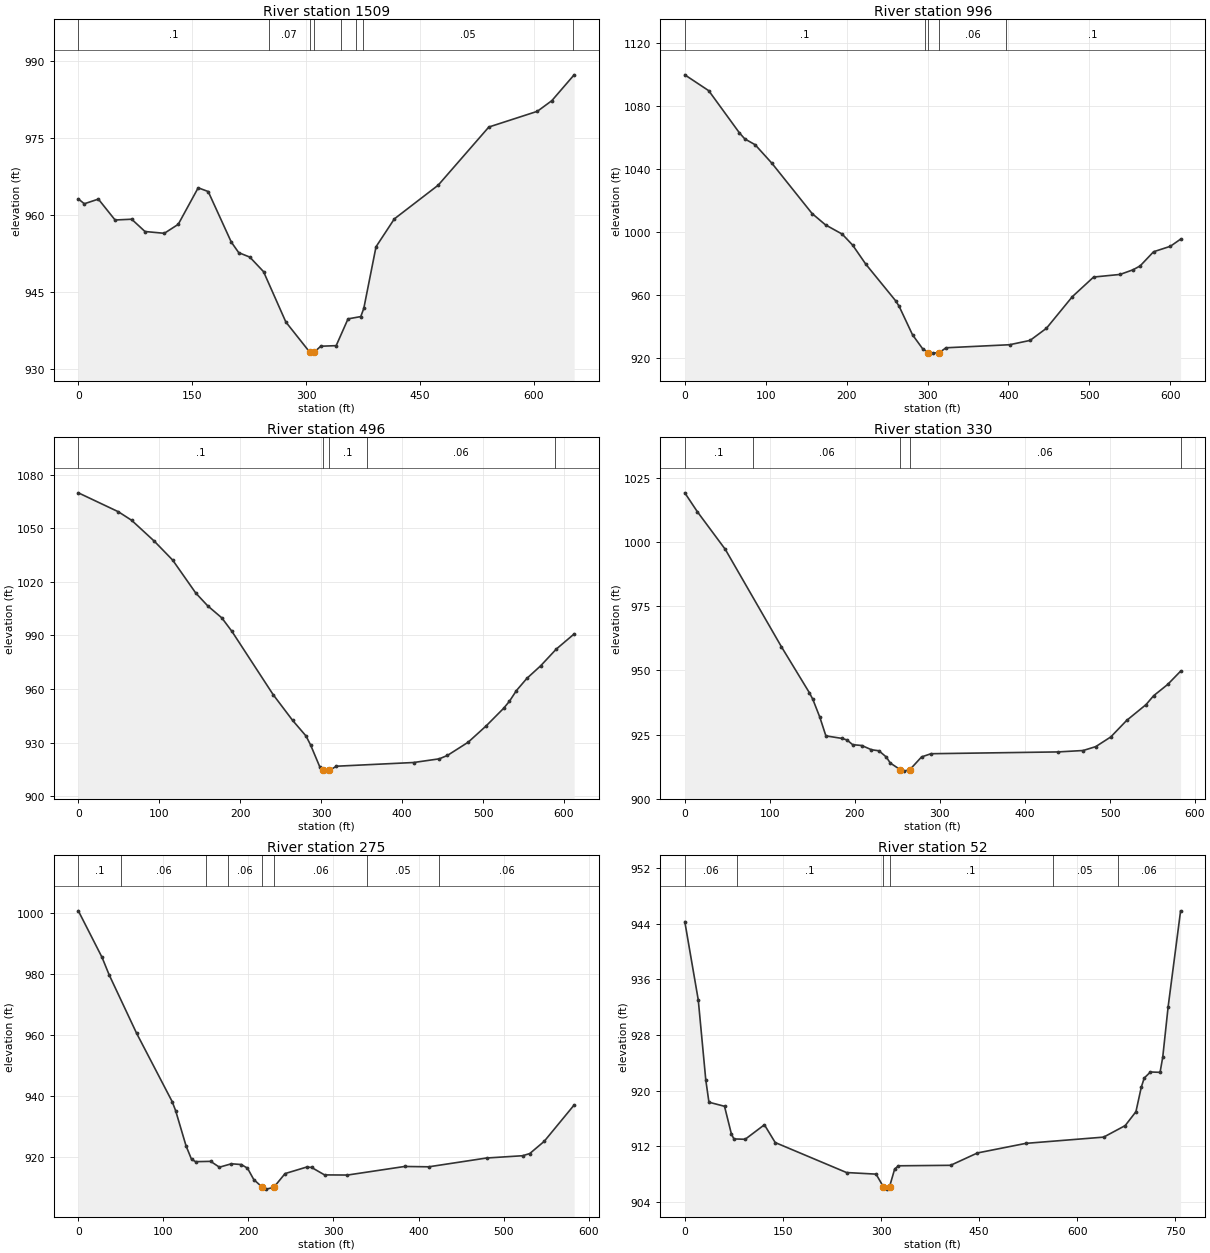
Type RM Length L Ch R = 1 ,1509    ,512.8,512.8,512.8
XS GIS Cut Line= 6
1680668.25303259 402694.822861181680434.43788342402590.206600592
1680326.56539576402571.4225174191680238.45139876402578.767319009
1680142.10283817402594.2518680841680043.56563367402618.833839923
#Sta/Elev= 30
       0  963.14     7.9  962.19    26.4   963.1    48.4  959.02    70.3  959.17
    87.8  956.77   113.3  956.42   131.6  958.17   157.9  965.31   171.1  964.58
   201.5  954.71   211.3  952.64   225.9  951.77     244  948.93   273.4  939.09
   304.7 933.232   307.2  933.01     311  933.23   319.4  934.36   339.7  934.47
   355.3   939.7   372.1  940.15   376.1  941.76   392.2  953.79   416.3  959.23
   474.1  965.82   540.8  977.18   604.7  980.25   623.8  982.33   653.2  987.38
#Mann= 8, -1 ,  0
       0     0.1       0  251.18    0.07       0   304.7   0.045       0
     311    0.07       0  346.15    0.05       0  365.65    0.06       0
  375.65    0.05       0  651.65     0.1       0
Bank Sta=304.7,311
XS Rating Curve= 0 ,0
Exp/Cntr(USF)=0,0
Exp/Cntr=0.3,0.1

Type RM Length L Ch R = 1 ,996     ,500,500,500
XS GIS Cut Line= 6
1680430.51039784402073.4943794161680341.39213775402103.207574591
1680256.78830434402125.5333173421680184.27073283402144.670746252
1679930.45988876402211.6505991671679839.81341651402235.571811169
#Sta/Elev= 30
       0 1099.75    29.6 1089.66    67.5 1062.85    74.2    1059    86.9 1055.33
   107.7 1043.51   157.3 1011.59   173.9 1004.37   194.5  998.51   207.4  991.52
   223.7  979.38   260.7  956.03   264.9  952.58   281.4  934.51   293.8  925.71
   301.1 923.171   306.2  922.85   314.5  923.17   322.8  926.25   401.4  928.19
   426.7  930.94   446.9  938.64     479  958.79   505.2  971.21   537.9  972.87
   553.8   975.8   562.7  978.29   579.3  987.29     600  990.75   612.7   995.3
#Mann= 5, -1 ,  0
       0     0.1       0  296.44    0.06       0   301.1   0.045       0
   314.5    0.06       0  396.44     0.1       0
Bank Sta=301.1,314.5
XS Rating Curve= 0 ,0
Exp/Cntr(USF)=0,0
Exp/Cntr=0.3,0.1

Type RM Length L Ch R = 1 ,496     ,166.5,166.5,166.5
XS GIS Cut Line= 6
1680145.47389442401560.4642375111680067.07575725401611.872599259
1679993.90464376401659.8541305961679784.84272592401796.941782922
1679711.67128435401844.9233142581679633.64847451401896.903525248
#Sta/Elev= 30
       0 1069.91    49.5  1059.3    65.8 1054.54    93.8 1042.85   116.6  1032.2
   145.1 1013.76   159.9 1006.57   177.3  999.84   189.8  992.26   240.8  956.78
   264.7  942.45   281.3  933.68     287  928.59   298.2  916.49   302.5914.3967
   307.3  914.01   310.1  914.39   318.8  916.76   414.2  918.84   445.9   920.9
     456  922.81   481.6  930.21   503.9  939.38   525.3  949.16   532.6  953.16
   541.2  959.13   554.1  965.96   571.1  972.99   590.5   982.4   612.5  990.84
#Mann= 5, -1 ,  0
       0     0.1       0   302.5   0.045       0   310.1     0.1       0
  356.25    0.06       0  588.75     0.1       0
Bank Sta=302.5,310.1
XS Rating Curve= 0 ,0
Exp/Cntr(USF)=0,0
Exp/Cntr=0.3,0.1

Type RM Length L Ch R = 1 ,330     ,55.5,55.5,55.5
XS GIS Cut Line= 6
1680026.43026837401542.620747977 1679865.2268621401503.353251576
1679798.10641382401607.0848534571679783.46195238401663.221955651
1679763.93600379401693.7312503221679588.20246648401787.699877908
#Sta/Elev= 30
       0 1019.19    14.7 1011.86    47.7  997.13   113.5  959.31   146.5  941.34
   150.6  938.73   158.8  931.78   165.9  924.54   184.9  923.55   190.7  922.95
   197.4  921.11   208.1  920.79   219.5  919.14   228.3  918.73     237  916.28
   241.6  913.97   253.1  911.43   257.8  910.81   264.7911.4045   278.4  916.34
   289.5  917.59   438.9  918.29   468.4  918.84   483.2  920.35   500.9  924.13
   519.6  930.57   542.3   936.7   551.3  940.18   567.8  944.56     583  949.74
#Mann= 5, -1 ,  0
       0     0.1       0      80    0.06       0   253.1   0.045       0
   264.7    0.06       0  582.99     0.1       0
Bank Sta=253.1,264.7
XS Rating Curve= 0 ,0
Exp/Cntr(USF)=0,0
Exp/Cntr=0.3,0.1

Type RM Length L Ch R = 1 ,275     ,222.2,222.2,222.2
XS GIS Cut Line= 6
 1679995.2536226401520.0438699211679834.05021632 401480.77637352
1679766.92976805401584.5079754011679752.28530661401640.645077595
1679732.75935802401671.1543722661679557.02582071401765.122999852
#Sta/Elev= 30
       0  1000.8    27.9  985.49    36.2  979.78    68.4  960.61   110.3   938.1
   114.4  935.11   126.7  923.49   133.1  919.11   137.9  918.33   155.6  918.43
   165.9  916.51   179.9  917.63   191.6  917.39   198.9  916.19   206.3  912.45
   216.3  909.92     221   909.3   229.8909.8892   243.1  914.41   268.4  916.55
   274.2  916.44   289.5  913.98   316.5  913.93   383.7  916.75   412.1  916.64
     480  919.53   522.4  920.28   530.8  920.99   547.8  925.01     583  936.96
#Mann= 8, -1 ,  0
       0     0.1       0      50    0.06       0     150     0.1       0
  175.92    0.06       0   216.3   0.045       0   229.8    0.06       0
  339.47    0.05       0  423.71    0.06       0
Bank Sta=216.3,229.8
XS Rating Curve= 0 ,0
Exp/Cntr(USF)=0,0
Exp/Cntr=0.3,0.1

Type RM Length L Ch R = 1 ,52      ,,,
XS GIS Cut Line= 4
1679918.20003744401475.164169932 1679712.7255877401328.809953422
1679618.71176116401403.2827650561679532.06536429401779.157275401
#Sta/Elev= 30
       0  944.32    20.6  933.04    32.1   921.5    36.9  918.32    60.7  917.73
    71.3  913.72    75.1  913.03    92.3  912.98   121.7  915.07   138.2  912.51
   247.2  908.19   292.4  907.96   303.4  906.16   309.5   905.8     313 906.163
   320.8  908.69   326.5  909.16   406.3  909.23   447.4  911.01   521.3  912.39
   640.3  913.29   673.2  914.95   689.6  916.95   697.8  920.48   702.3   921.8
   711.8  922.67   726.5  922.62   730.6  924.81   738.8  932.03   757.9  945.88
#Mann= 6, -1 ,  0
       0    0.06       0      80     0.1       0   303.4   0.045       0
     313     0.1       0   562.2    0.05       0   662.2    0.06       0
Bank Sta=303.4,313
XS Rating Curve= 0 ,0
Exp/Cntr(USF)=0,0
Exp/Cntr=0.3,0.1
LCMann Table=0

Chan Stop Cuts=-1
Use User Specified Reach Order=0
Composite Channel Slope=5